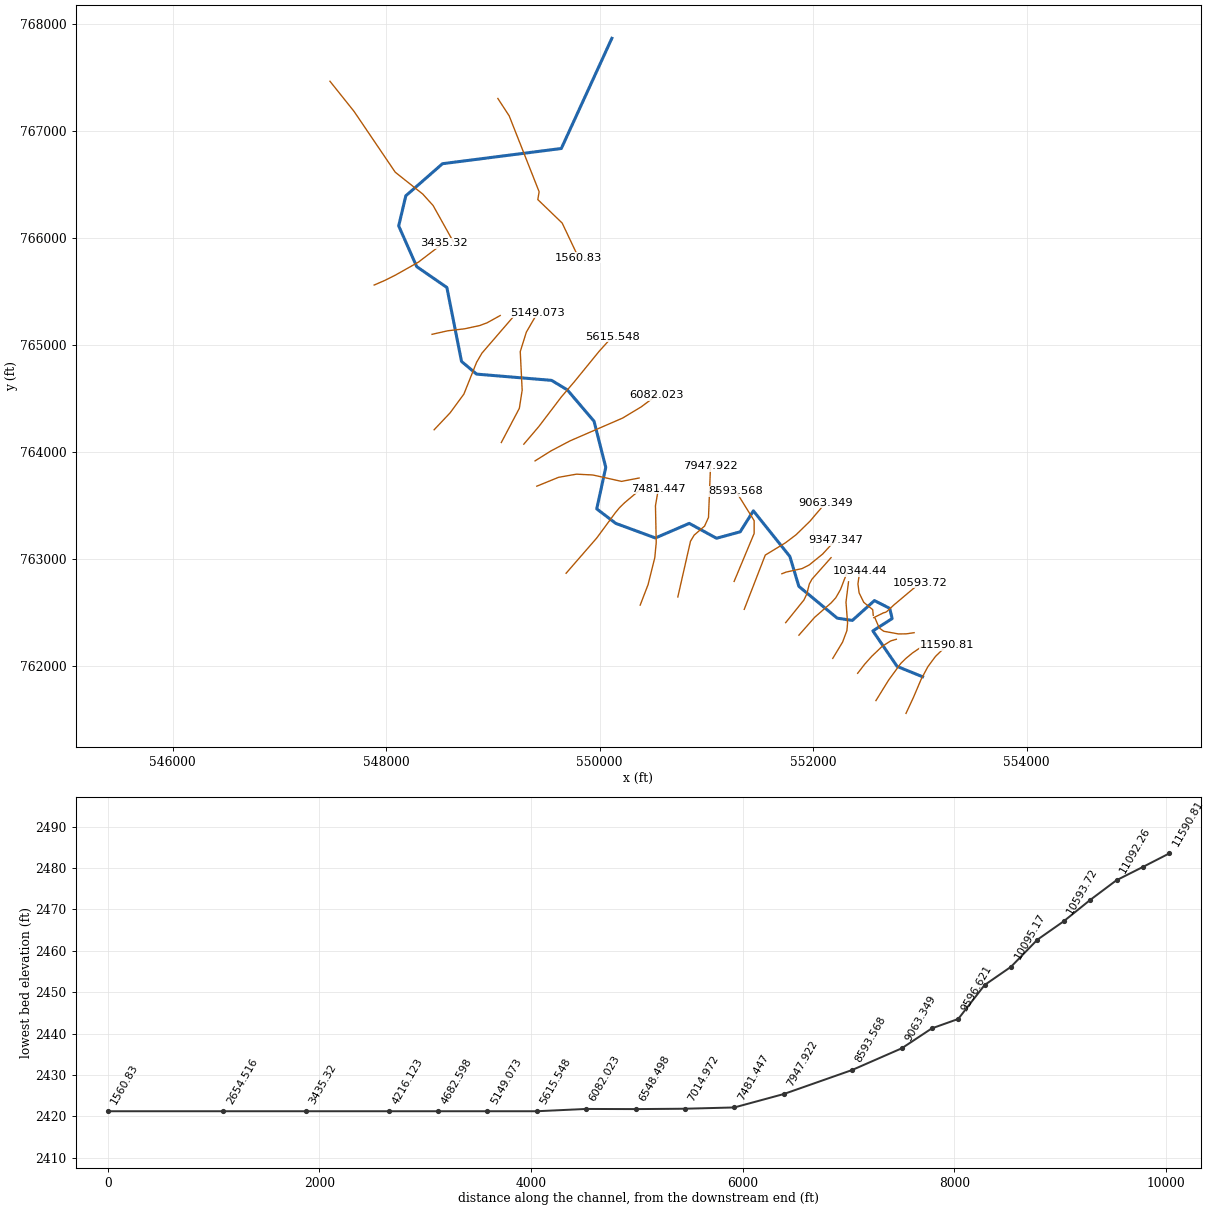
--- 10829_ras.prj (project) ---

Proj Title=10829
Current Plan=p01
Default Exp/Contr=0.3,0.1
English Units
Geom File=g01
Flow File=f01
Plan File=p01
Y Axis Title=Elevation
X Axis Title(PF)=Main Channel Distance
X Axis Title(XS)=Station
BEGIN DESCRIPTION:
RFD model 10829 exported to HEC-RAS
END DESCRIPTION:

--- 10829_ras.p01 (plan) ---

Plan Title=Plan 01
Program Version=4.10
Short Identifier=Plan 01
Geom File=g01
Flow File=f01
Subcritical Flow
Calc Critical at every XS
Secant Critical Depth

--- 10829_ras.f01 (steady flow) ---

Flow Title=Flow 01
Program Version=5.01
Number of Profiles= 6
Profile Names=10yr,25yr,50yr,100yr,100plus,500yr
River Rch & RM=10829,24,11590.81
  722.68 1105.83 1451.78 1746.23  2549.5 3433.97
River Rch & RM=10829,24,11341.54
  730.15 1117.34 1466.96 1764.54 2576.23 3465.05
River Rch & RM=10829,24,11092.26
  734.25 1123.65 1475.29 1774.59  2590.9 3482.09
River Rch & RM=10829,24,10842.99
  740.19  1132.8 1487.36 1789.17 2612.18 3506.83
River Rch & RM=10829,24,10593.72
  740.92 1133.94 1488.87 1790.98 2614.84 3509.91
River Rch & RM=10829,24,10344.44
 1233.98    1892 2488.32 2995.36 4373.22 5464.28
River Rch & RM=10829,24,10095.17
 1238.87  1899.6  2498.4 3007.58 4391.06 5483.73
River Rch & RM=10829,24,9845.895
 1242.74 1905.62 2506.41  3017.3 4405.26 5499.26
River Rch & RM=10829,24,9596.621
 1245.64 1910.14 2512.41 3024.59  4415.9  5510.9
River Rch & RM=10829,24,9347.347
 1507.72 2314.86  3047.7 3671.14 5359.87 6515.47
River Rch & RM=10829,24,9063.349
  1528.7 2347.57 3091.23 3724.01 5437.05 6597.57
River Rch & RM=10829,24,8593.568
 1647.17 2532.71 3338.01 4024.14 5875.24 7062.17
River Rch & RM=10829,24,7947.922
 1791.21 2756.53 3635.27 4384.45 6401.29 7608.67
River Rch & RM=10829,24,7481.447
 1802.84 2774.79 3659.68  4414.2 6444.73 7654.17
River Rch & RM=10829,24,7014.972
 1830.62 2818.29 3717.76 4484.93 6547.99 7761.81
River Rch & RM=10829,24,6548.498
  1908.7 2940.38 3880.59    4683 6837.19 8061.26
River Rch & RM=10829,24,6082.023
 1963.54 3026.89 3996.61 4824.84 7044.26 8277.22
Boundary for River Rch & Prof#=10829,24,1
Up Type= 0
Dn Type= 2
Boundary for River Rch & Prof#=10829,24,2
Up Type= 0
Dn Type= 2
Boundary for River Rch & Prof#=10829,24,2
Up Type= 0
Dn Type= 2
Boundary for River Rch & Prof#=10829,24,2
Up Type= 0
Dn Type= 2
Boundary for River Rch & Prof#=10829,24,2
Up Type= 0
Dn Type= 2
Boundary for River Rch & Prof#=10829,24,2
Up Type= 0
Dn Type= 2

--- 10829_ras.g01 (geometry) ---

Geom Title=10829
Program Version=4.10

River Reach=10829,24
Reach XY= 30
 553025.16373381761898.357294828  552786.8824839761994.711461499
552559.885956019762326.308683708552740.441511571762441.760072604
552717.438039362762537.246183723552574.208872676762609.728822619
552367.177622676762424.398961484552225.684567124762445.666322619
551866.309567213762742.541322619551782.108178228763021.621183708
551440.094289362763448.270489261551316.830400527763252.523961499
551094.608178228763192.194100395550839.399844915763331.082989261
550522.125539362763194.798267052550150.684567124763331.082989261
549972.559567124763466.499655932550056.934567124763854.520489275
549947.212344915764285.423267066549696.517900467764578.478822604
549549.295678228764667.367711499548846.517900467764725.701044843
548705.429937512764844.242711499548568.277159721765535.214933723
548285.697570771765729.827599734548116.730179757766110.382015079
548183.451457381766391.644335896  548527.3311176766691.592257202
549640.453817457766833.712763026550113.973050922767862.934841126

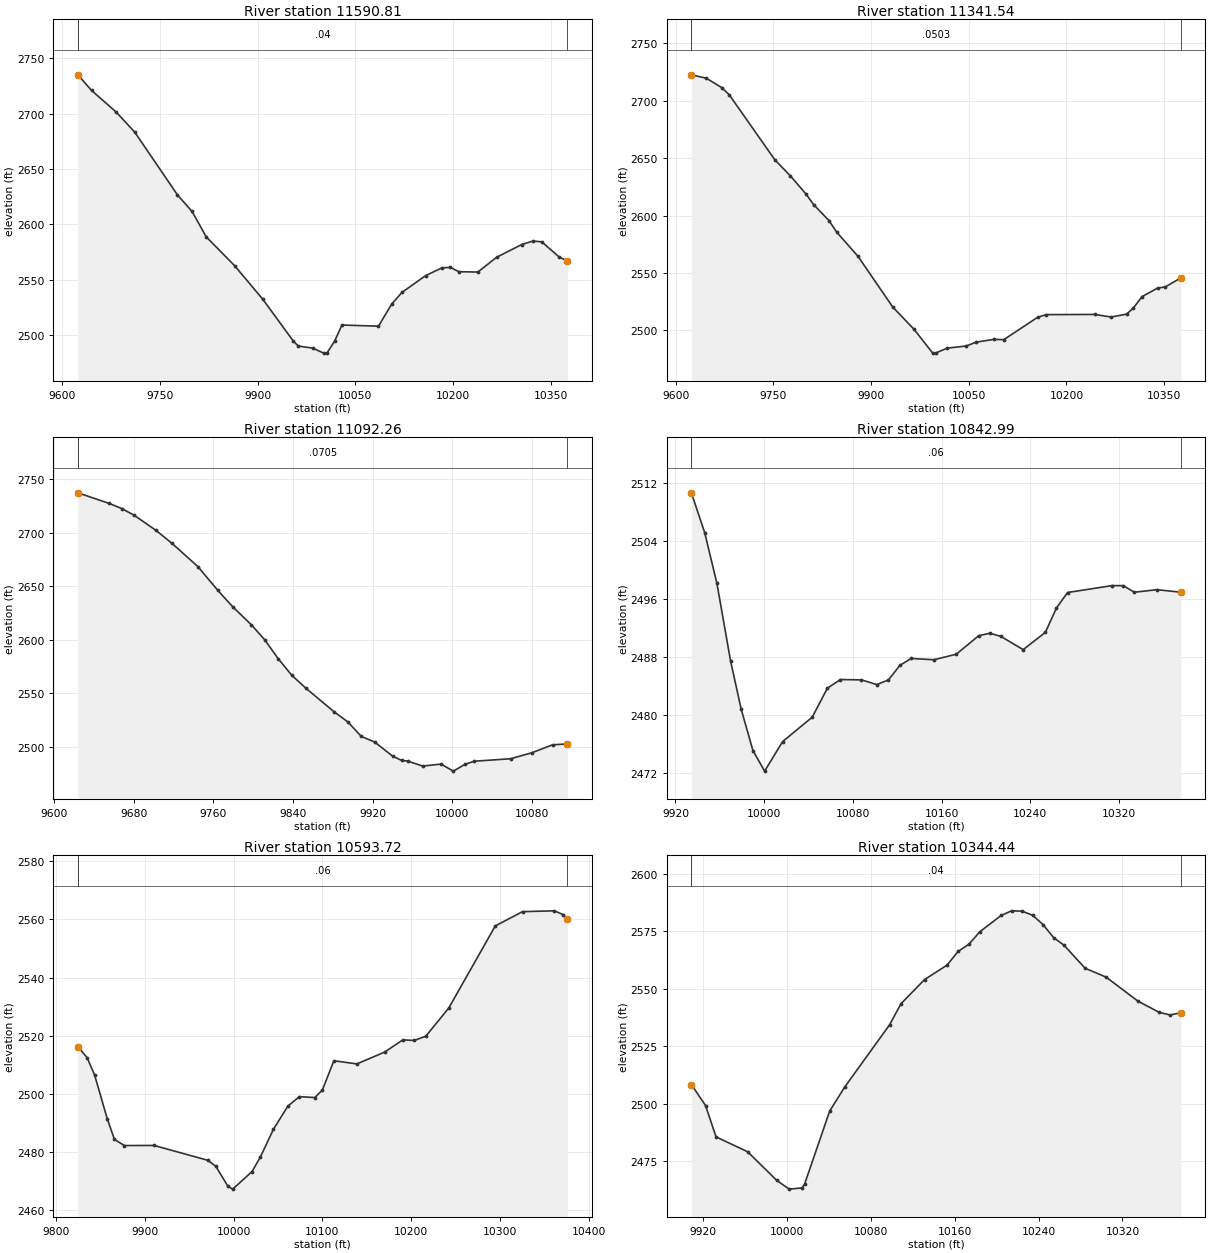
Type RM Length L Ch R = 1 ,11590.81,249.274000,249.274000,249.274000
XS GIS Cut Line= 6
552870.228587436761555.948351569552939.114222184761703.255617708
 553012.51346145761875.463151446553075.095390397761991.964415732
553146.632564762762088.364535442553254.270758084762192.211299622
#Sta/Elev= 30
9624.0232734.9679645.0552720.8219682.5012701.5069711.2912683.2269776.9292626.492
9799.4082611.5079821.1492588.5659864.6312562.6179908.1132532.1359954.6762494.583
9962.4652489.9529984.5122488.05710001.532483.53710006.982483.94610018.292494.374
 10029.62508.922 10085.7 2507.8910105.922527.82410121.862538.447 10158.12553.532
10183.11 2560.5910196.052560.99310208.992557.114 10238.32556.77610267.032570.102
10305.472581.59610323.022584.776 10336.52584.09410363.442570.26310375.932566.821
#Mann= 3 , 0 , 0
9624.023    0.04       09624.023    0.04       010375.93    0.04       0
#XS Ineff= 2 , 0
       0                               0
Bank Sta=9624.023,10375.93
Exp/Cntr=0.3,0.1

Type RM Length L Ch R = 1 ,11341.54,249.274000,249.274000,249.274000
XS GIS Cut Line= 6
552588.436044248761675.256128262552706.450708789761865.429701263
552820.591962634762021.776750772552866.548210646762067.119619151
552928.982224184762118.855182727553085.063546363762224.929030886
#Sta/Elev= 30
9624.025 2722.66 9647.072719.7029670.4142711.5829682.0862705.3629752.308 2648.57
9776.0692634.661 9799.832619.0249811.711 2609.699835.4722595.6359847.3522585.542
9879.8492564.6299933.2592520.4649966.0672500.9759994.6342480.346    99992480.266
10016.992484.645 10046.12486.44610061.752489.89810088.82 2492.25 10103.92492.003
10156.01 2511.53   101692513.79910243.852513.96610268.492511.69410292.362514.202
10302.652519.42610316.212529.50810340.072536.89610351.992537.97910375.922545.832
#Mann= 3 , 0 , 0
9624.025  0.0503       09624.025  0.0503       010375.92  0.0503       0
#XS Ineff= 2 , 0
       0                               0
Bank Sta=9624.025,10375.92
Exp/Cntr=0.3,0.1

Type RM Length L Ch R = 1 ,11092.26,249.274000,249.274000,249.274000
XS GIS Cut Line= 6
552417.064210933761930.386061469552484.148092549762016.532930729
552548.165970947762088.048303051552646.873662347762181.990290388
552726.445773934762232.938975458552779.627718977762248.259918647
#Sta/Elev= 30
9624.0572737.4939655.2542727.6719667.928 2722.829680.6032716.5049702.0782702.614
9718.3542690.4139744.6072668.4319764.5072646.303  9779.52630.9159798.2922613.979
9811.7132599.9529825.1352582.388 9838.852566.7899853.3012554.4339881.0992532.813
9895.1122523.1559908.6852509.5839922.2572504.1779940.3882490.9259949.4022487.022
9955.1782486.502  9970.32481.793 9988.842483.65610001.08 2477.0610012.932483.468
10022.112486.31910058.672488.65510079.862494.219 10100.82501.69310115.74 2502.52
#Mann= 3 , 0 , 0
9624.057  0.0705       09624.057  0.0705       010115.74  0.0705       0
#XS Ineff= 2 , 0
       0                               0
Bank Sta=9624.057,10115.74
Exp/Cntr=0.3,0.1

Type RM Length L Ch R = 1 ,10842.99,249.274000,249.274000,249.274000
XS GIS Cut Line= 6
552580.104128419762445.881846719552619.406052737762354.062439972
 552661.79009834762322.998703968  552800.1672871762298.171281047
 552872.43684617762298.914059941 552946.34967207762309.789080761
#Sta/Elev= 30
9934.3442510.6699946.3392505.1859957.363 2498.18 9969.742487.4429979.2792480.817
9989.8572475.11810000.412472.28610016.612476.36110043.352479.729   100572483.733
10068.782484.91710087.732484.87110101.592484.22110112.082484.86510122.35 2486.87
10132.592487.82610153.032487.64710173.242488.41610193.452490.96410203.482491.308
10213.522490.85910233.572489.04210253.582491.43310263.582494.79310273.582496.921
10313.692497.87310323.752497.86510333.812496.95910354.112497.313 10375.82496.958
#Mann= 3 , 0 , 0
9934.344    0.06       09934.344    0.06       0 10375.8    0.06       0
#XS Ineff= 2 , 0
       0                10204.53       0
Bank Sta=9934.344,10375.8
Exp/Cntr=0.3,0.1

Type RM Length L Ch R = 1 ,10593.72,249.274000,249.274000,249.274000
XS GIS Cut Line= 6
552568.072917014 762450.39684324552660.191777647762495.763828546
552677.450522542  762500.0830663552689.148952931762506.605600804
552759.520986021762571.213089734553006.166406095762778.055068597
#Sta/Elev= 30
9824.6622516.2089835.0812512.406 9843.532506.4049857.7152491.3899865.8242484.266
9876.9712482.1619910.4122482.189 9970.962477.0829980.0252474.9979993.5842468.152
    9999 2467.1510020.722473.18910030.142478.181 10044.92487.78510061.162495.754
10074.112498.99210091.512498.694   101002501.28110112.952511.37110138.852510.269
10170.22 2514.3610190.642518.55610203.582518.34410216.53 2519.8310242.432529.573
10294.722557.78610325.362562.70110361.242562.986 10371.32561.65810375.982560.014
#Mann= 3 , 0 , 0
9824.662    0.06       09824.662    0.06       010375.98    0.06       0
#XS Ineff= 2 , 0
       0                               0
Bank Sta=9824.662,10375.98
Exp/Cntr=0.3,0.1

Type RM Length L Ch R = 1 ,10344.44,249.273900,249.273900,249.273900
XS GIS Cut Line= 6
552563.267133296762471.542291805 552558.25742048762524.981980741
  552474.3884525 762593.40414618552430.676502973 762682.18189536
552420.065752685 762764.85775958552436.216492176762885.173615038
#Sta/Elev= 30
9908.4932508.2699922.009 2499.139932.0532485.4569962.167 2478.999989.9692466.498
10001.862462.68810013.962463.20210016.482464.75710040.54 2496.7510054.852507.189
 10097.7 2534.3210108.692543.55710131.092554.04610152.572560.33610163.082566.288
10173.512569.46210183.742574.84310204.132581.96210214.162583.99710224.192583.851
10234.232582.06910244.262577.96810254.292572.315 10264.32568.97310284.33 2558.97
 10304.42555.09810334.822544.61910355.232539.72210365.432538.60510375.822539.572
#Mann= 3 , 0 , 0
9908.493    0.04       09908.493    0.04       010375.82    0.04       0
#XS Ineff= 2 , 0
       0                               0
Bank Sta=9908.493,10375.82
Exp/Cntr=0.3,0.1

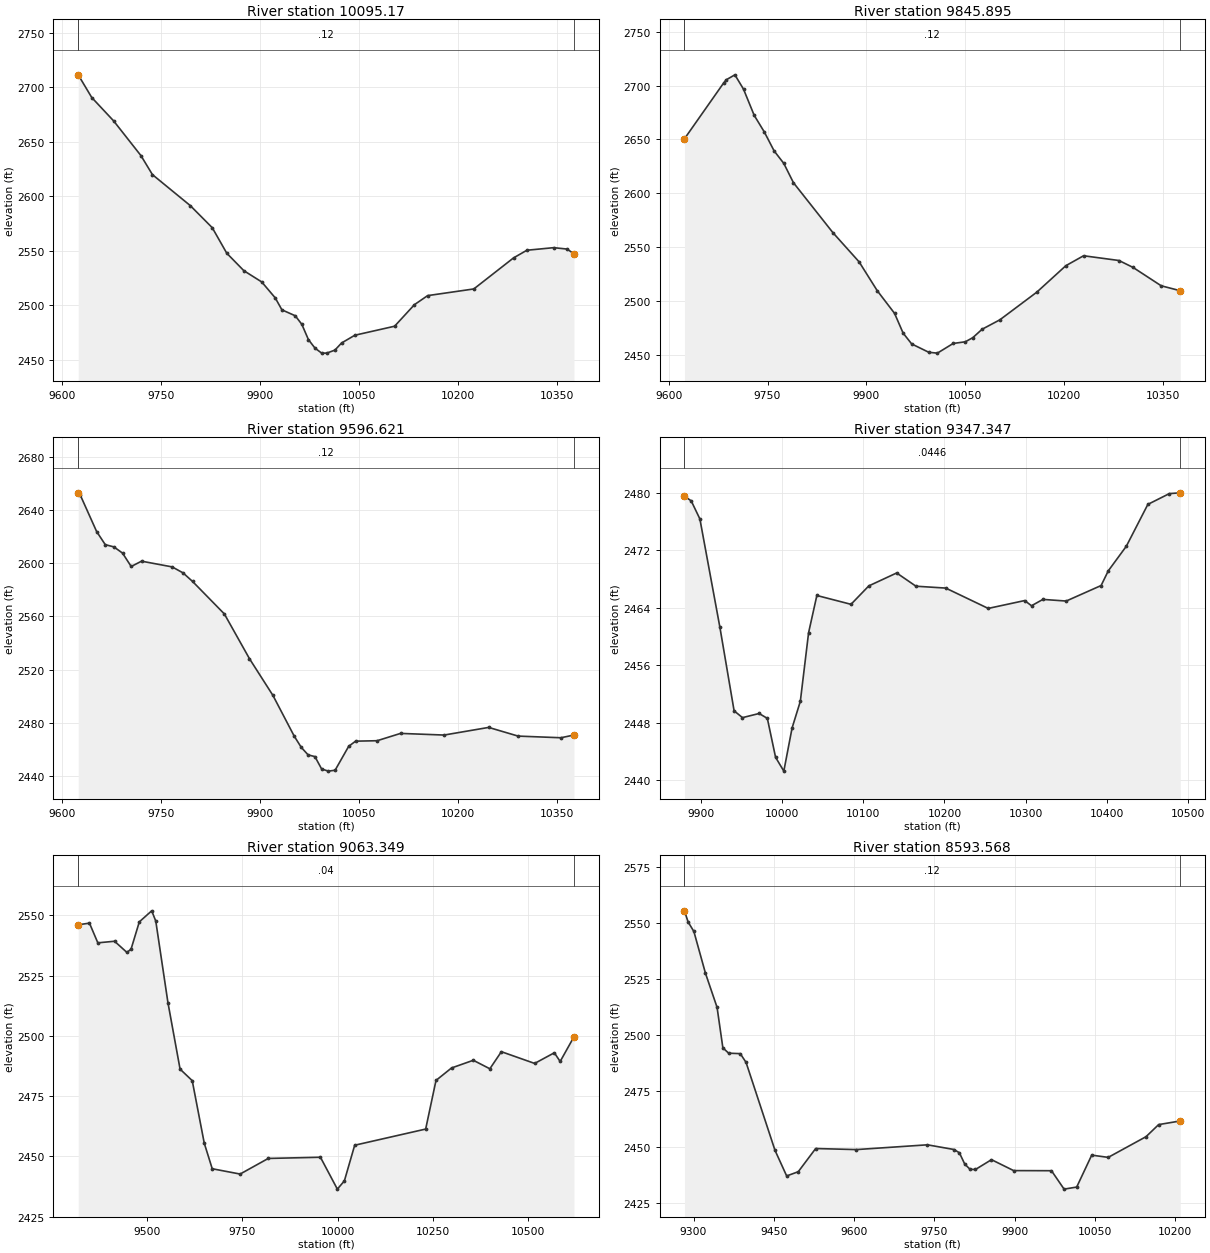
Type RM Length L Ch R = 1 ,10095.17,249.274000,249.274000,249.274000
XS GIS Cut Line= 6
552183.999594455762069.676439906552275.824293229762221.686881756
552316.776114804 762330.08968965 552322.63116197762399.667670524
552307.891360869762596.125390091552331.579191265762785.193396687
#Sta/Elev= 30
9624.1092711.3139644.6422690.5199677.7852669.1019719.307 2637.199736.6722619.812
9794.0812591.4019827.4032571.1419849.4032547.7459875.3022531.7339902.4022521.421
 9922.922506.7819933.0232495.8399953.2242490.4069963.2272482.561 9973.232468.522
9983.2342460.7129993.2552456.166   100012456.14410013.422458.92310023.472465.433
10043.582472.549 10103.92480.80710133.972500.57210153.982508.86710224.042514.991
10284.342543.48110304.54 2550.4810345.172552.83910365.542551.55410375.932547.146
#Mann= 3 , 0 , 0
9624.109    0.12       09624.109    0.12       010375.93    0.12       0
#XS Ineff= 2 , 0
       0                               0
Bank Sta=9624.109,10375.93
Exp/Cntr=0.3,0.1

Type RM Length L Ch R = 1 ,9845.895,249.274000,249.274000,249.274000
XS GIS Cut Line= 6
551866.665649662762286.684081162552013.508521594762452.654221879
552167.352951165762586.973369436552212.234721357762636.040388711
552256.538135024762713.261989117552317.661005217762872.038813938
#Sta/Elev= 30
9624.0442650.6399683.3512702.3199687.3662705.3239700.4722709.9389713.5782696.626
9729.7642672.3459745.2352656.7849759.9962639.3319774.6472627.7759789.2972609.834
9849.1412563.5129888.9052536.3879916.3362509.6969942.6332488.6459955.6172470.321
9968.6012460.273 9994.572452.51210007.592451.74110031.522460.70210050.032462.279
10061.332466.10610075.412473.897 10102.32482.63310158.362508.30610202.382532.848
 10229.32542.08110282.962537.67210304.322531.25510347.042514.20910375.922509.623
#Mann= 3 , 0 , 0
9624.044    0.12       09624.044    0.12       010375.92    0.12       0
#XS Ineff= 2 , 0
       0                               0
Bank Sta=9624.044,10375.92
Exp/Cntr=0.3,0.1

Type RM Length L Ch R = 1 ,9596.621,249.274000,249.274000,249.274000
XS GIS Cut Line= 6
551742.904309418762403.698534396551914.017153277762615.658030223
551940.707169672762671.282757453551964.255985467762764.684415668
551988.647792245 762809.54658404552168.105918051763010.905077399
#Sta/Elev= 30
9624.0652653.0239627.3072651.2239651.9822623.9139665.0882614.0199678.1942612.324
  9691.32607.6559704.406 2597.579720.1322601.5739766.545 2597.279783.0412592.771
9797.4862586.3179845.7172561.864 9883.812528.1689919.3892500.5229951.6942469.845
 9962.342461.4359972.7142455.7819983.0652454.4659993.2642445.13410003.462443.544
10013.672444.21810034.252462.20910044.752466.09910077.362466.42910112.93 2471.94
10178.912470.69710246.582476.449 10291.22469.90910356.182468.66910375.932470.723
#Mann= 3 , 0 , 0
9624.065    0.12       09624.065    0.12       010375.93    0.12       0
#XS Ineff= 2 , 0
       0                               0
Bank Sta=9624.065,10375.93
Exp/Cntr=0.3,0.1

Type RM Length L Ch R = 1 ,9347.347,283.997900,283.997900,283.997900
XS GIS Cut Line= 6
551707.269891798762860.817884708551748.087103086762876.242616307
551897.019944861762909.168620942551963.762605852762942.892847229
552089.000830702763044.370063226552209.228426427763175.123810481
#Sta/Elev= 30
9879.9152479.5389888.1792478.8959898.8692476.376 9923.552461.2669940.9942449.667
9951.3082448.7159971.7682449.292 9981.912448.6149992.0522443.196 10002.22441.269
10012.372447.27210022.542450.99310032.712460.54510042.88 2465.7210084.912464.491
10106.812467.05410141.132468.85610164.872467.01210201.522466.75210253.84 2463.92
10298.722465.01410307.132464.29210321.162465.17510349.842464.94610392.842467.109
10401.642469.14910423.892472.58110450.372478.40310476.862479.90510490.262480.012
#Mann= 3 , 0 , 0
9879.915  0.0446       09879.915  0.0446       010490.26  0.0446       0
#XS Ineff= 2 , 0
       0                               0
Bank Sta=9879.915,10490.26
Exp/Cntr=0.3,0.1

Type RM Length L Ch R = 1 ,9063.349,469.780800,469.780800,469.780800
XS GIS Cut Line= 6
551354.488019409762528.076815585551551.426285615763034.662992964
551740.532110567763149.544518166551840.637583559763225.177992306
551970.170332441763351.136409073552117.992939409763524.891375879
#Sta/Elev= 30
9319.1342546.0569348.6962546.7369370.6552538.5749414.5752539.2289447.0972534.593
 9457.932535.9689479.597 2547.279512.0962551.8429522.825 2547.599554.7232513.803
9586.6222486.2129618.5212481.4419650.1052455.5189671.0372444.9089744.2982442.708
 9818.152449.1819955.1462449.6769999.5852436.45910018.032439.88910045.072454.658
10231.442461.35910258.592481.52510299.322486.69110356.56 2489.8810399.992486.357
10430.22 2493.4410517.592488.57510569.292492.98710584.572489.37810620.862499.629
#Mann= 3 , 0 , 0
9319.134    0.04       09319.134    0.04       010620.86    0.04       0
#XS Ineff= 2 , 0
       0 9874.62                       0
Bank Sta=9319.134,10620.86
Exp/Cntr=0.3,0.1

Type RM Length L Ch R = 1 ,8593.568,645.645900,645.645900,645.645900
XS GIS Cut Line= 4
551259.710934997762788.825194418 551447.13650164763236.673653707
 551447.13650164763357.020596534551277.467041314763629.280893371
#Sta/Elev= 30
9283.1342555.2469289.8272550.3029300.6682546.0529322.3492527.4219344.0292512.226
 9354.872494.183 9365.712491.7919387.3912491.5979398.2312487.6829452.2512448.534
9474.1142437.0819495.7952438.9699528.3162449.3049604.1992448.8289737.1832450.956
9786.9462448.8619796.9462447.4029806.9462442.3819816.9462440.0269826.9462439.957
9856.9462444.3379898.3692439.4639969.0662439.4149992.6322431.206 10016.22432.125
10044.272446.35710075.112445.35810145.812454.58410169.372459.96710209.772461.585
#Mann= 3 , 0 , 0
9283.134    0.12       09283.134    0.12       010209.77    0.12       0
#XS Ineff= 2 , 0
       09670.384                       0
Bank Sta=9283.134,10209.77
Exp/Cntr=0.3,0.1

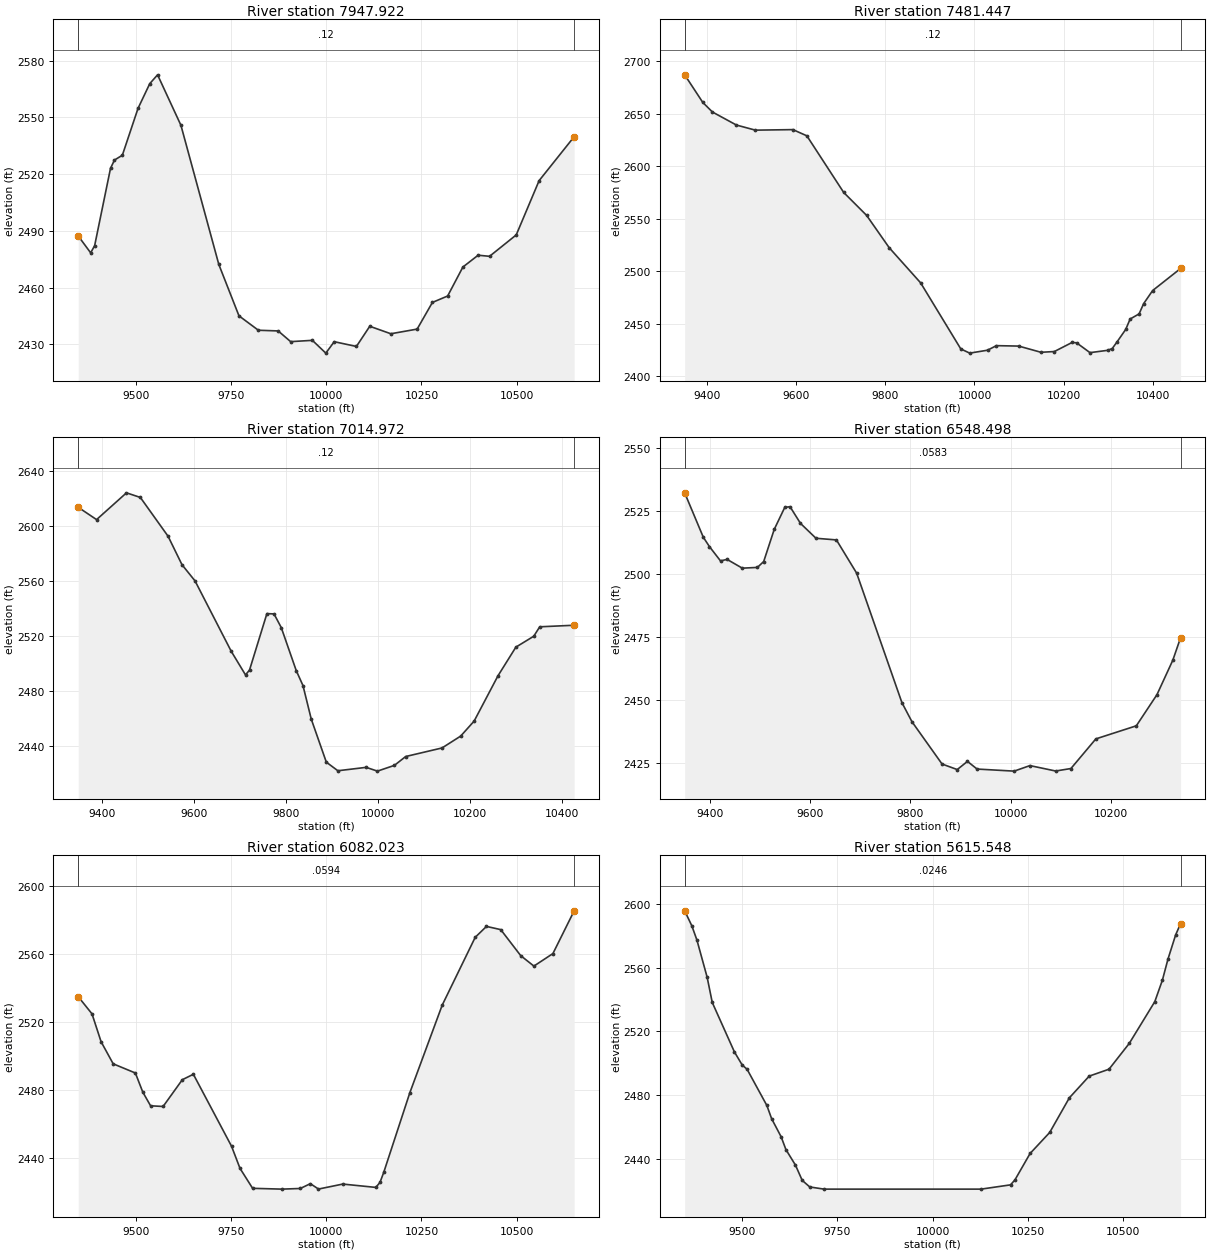
Type RM Length L Ch R = 1 ,7947.922,466.474900,466.474900,466.474900
XS GIS Cut Line= 6
550732.216714467762643.645617816550850.816606063763164.132804763
550884.840188428763220.821982317550982.712864427763305.476134054
551019.571141971763386.769053154551038.626710698763866.513996562
#Sta/Elev= 30
 9349.17 2487.339381.8322478.4179392.2492482.1689433.9182523.0649444.3352527.449
9465.0062529.9939506.2182554.795 9537.012567.8449557.4452572.494 9618.732545.835
9718.2082472.262 9771.082445.1129822.0492437.4959873.9692437.1349906.7592431.472
9963.7422432.162    99992425.40410021.112431.44610079.312428.93210114.372439.596
10169.672435.64410238.712438.10210278.762452.19710318.772455.59610358.772470.902
10398.782477.15710428.782476.57210498.792487.88310558.852516.57510650.792539.786
#Mann= 3 , 0 , 0
 9349.17    0.12       0 9349.17    0.12       010650.79    0.12       0
#XS Ineff= 2 , 0
       0                               0
Bank Sta=9349.17,10650.79
Exp/Cntr=0.3,0.1

Type RM Length L Ch R = 1 ,7481.447,466.474900,466.474900,466.474900
XS GIS Cut Line= 6
550379.611203603 762567.29967977550453.395616229 762758.79486008
550516.395790801763011.168753568550529.894286251763152.162252118
550522.691229341763496.398321264 550550.08698696  763655.7867374
#Sta/Elev= 30
9349.1192686.898 9389.812660.6339411.3962651.5369465.3612639.1199507.9232634.271
9592.2212634.777 9623.572628.8639706.3192574.9949757.7112553.2159808.5032522.441
9879.0692489.0249969.2992426.1629989.299 2422.1710029.322424.95110049.32 2429.28
10099.34 2428.8710149.382422.978 10179.42423.68110219.432432.35710229.442431.959
10259.45 2422.6310299.462424.85410309.492426.56410319.542432.42810339.622444.648
10349.662454.626 10369.8  2459.510379.942469.21310400.212481.69710463.042502.691
#Mann= 3 , 0 , 0
9349.119    0.12       09349.119    0.12       010463.04    0.12       0
#XS Ineff= 2 , 0
       0                               0
Bank Sta=9349.119,10463.04
Exp/Cntr=0.3,0.1

Type RM Length L Ch R = 1 ,7014.972,466.474800,466.474800,466.474800
XS GIS Cut Line= 6
549685.402948654762865.176374766549972.439627171763194.448655937
550147.115452167763430.975770665550186.008381411763477.851952998
550232.517141824763523.123364775550401.265136047763664.944019213
#Sta/Elev= 30
9349.0242613.594  9388.92604.633 9453.872624.097    94842620.7439544.2582592.512
9574.3882571.887 9602.83 2560.069681.4332508.9139712.405 2491.789721.1112495.317
9758.864 2536.32 9774.352536.0949790.0422526.1949822.6162494.8969837.2462484.032
9855.1912459.6959887.923 2428.399913.0022422.1329974.4122424.5969998.977 2421.86
 10035.82426.04310060.352432.477 10139.32438.703 10179.8 2447.33   102092458.232
10260.812491.14410299.66 2511.9610338.522519.89510351.472526.73410426.242527.871
#Mann= 3 , 0 , 0
9349.024    0.12       09349.024    0.12       010426.24    0.12       0
#XS Ineff= 2 , 0
       0                               0
Bank Sta=9349.024,10426.24
Exp/Cntr=0.3,0.1

Type RM Length L Ch R = 1 ,6548.498,466.474900,466.474900,466.474900
XS GIS Cut Line= 6
549410.626693389763678.511764481549614.615683947 763761.45764709
549782.475700032763790.953763551549935.780222893 763783.25690466
550204.492026316763723.490159172550369.380302682763754.971784054
#Sta/Elev= 30
9349.114 2532.139386.3252514.5119398.6122510.7979420.6572505.1419433.7972505.734
9464.1732502.2579494.3032502.5499506.9122504.8849527.9682517.6399549.0232526.374
9559.5512526.6219580.4142520.0079611.3422514.112 9652.172513.4549692.603 2500.26
9782.9342448.947 9802.942441.3859863.1132424.593 9893.412422.3929913.8662425.634
9933.0822422.59410007.142421.77310038.582423.96710090.042421.81610120.512422.808
10170.262434.557 10251.12439.74410292.262452.07610323.982465.76410339.552474.713
#Mann= 3 , 0 , 0
9349.114  0.0583       09349.114  0.0583       010339.55  0.0583       0
#XS Ineff= 2 , 0
       0                               0
Bank Sta=9349.114,10339.55
Exp/Cntr=0.3,0.1

Type RM Length L Ch R = 1 ,6082.023,466.474900,466.474900,466.474900
XS GIS Cut Line= 6
549394.659546072763915.106332968549542.947135284764007.785545317
549722.109790912 764101.97470893550215.224086301764315.161293627
550389.132982785764419.718047383 550536.72427644764529.297559294
#Sta/Elev= 30
 9349.042535.0119385.2262524.888 9409.08 2508.519440.8332495.5029499.1022490.099
9518.5252478.8919538.9842470.8199571.8532470.415 9622.422486.1729651.336 2489.35
9751.6552446.9849773.7382434.0269806.8632422.283 9883.442421.8079932.0662422.185
  9958.52425.0129979.8222421.84810043.622424.78110130.182422.82210141.192425.722
10151.152431.70610219.632478.51910304.582530.01710391.232569.91310420.782576.325
10458.242574.42710510.752559.109 10545.32552.98210595.212560.34710650.952585.483
#Mann= 3 , 0 , 0
 9349.04  0.0594       0 9349.04  0.0594       010650.95  0.0594       0
#XS Ineff= 2 , 0
       0                               0
Bank Sta=9349.04,10650.95
Exp/Cntr=0.3,0.1

Type RM Length L Ch R = 1 ,5615.548,466.474900,466.474900,466.474900
XS GIS Cut Line= 6
549289.071386706764071.064947556549429.828440376764235.733178901
549639.842133983764511.216763555549763.531062668764655.681143346
549993.974924796764937.715641776550117.639078891765074.501834383
#Sta/Elev= 30
9349.0352595.489 9367.742586.1449381.1622577.2059408.0082553.9139421.4312538.123
9479.6242507.1479499.8972499.0239512.8682496.2969564.7542473.6399577.2972465.349
9602.3132453.9969614.8212446.0119639.838  2436.39657.5512426.7549677.3622422.615
9714.8872421.255 10127.22421.255 10204.42423.92810215.92 2426.9910255.862443.586
10307.332456.73810358.892478.40610410.962491.99810463.022496.33410516.172512.496
10583.222538.63510603.182552.11310617.832565.31110637.972580.44410650.982587.525
#Mann= 3 , 0 , 0
9349.035  0.0246       09349.035  0.0246       010650.98  0.0246       0
#XS Ineff= 2 , 0
       0                               0
Bank Sta=9349.035,10650.98
Exp/Cntr=0.3,0.1

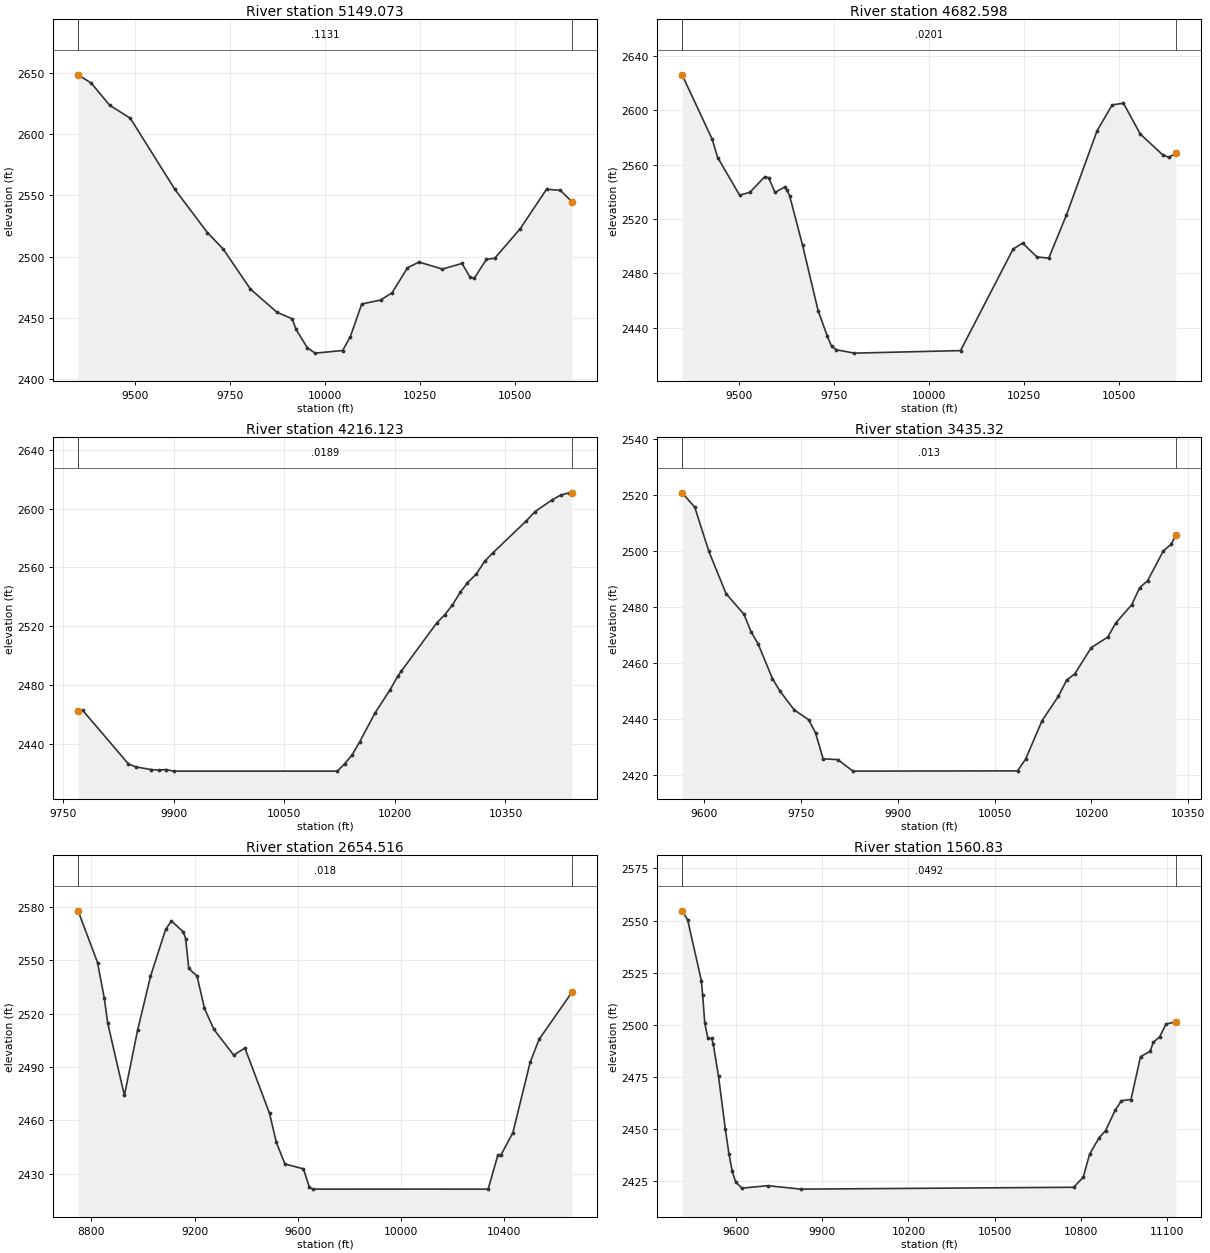
Type RM Length L Ch R = 1 ,5149.073,466.474800,466.474800,466.474800
XS GIS Cut Line= 6
549078.424021527764086.795178105549247.318243349764406.397274674
549273.727700832764575.833019064549255.742375213764935.939457463
549312.814906641765118.039321185549418.779893725765299.944685625
#Sta/Elev= 30
9349.1112648.5399383.7512641.7889432.6272623.6099486.6262613.1239604.0892555.095
9689.9512519.6979731.7062506.2639803.3042473.6049873.6342454.5849913.6522449.296
9923.6732440.6879953.8352425.436 9974.242421.25510046.632423.39510066.782434.637
10096.932461.36510146.972464.65310177.082470.61110217.49  2490.910247.792495.654
10309.522489.90810361.332494.48810382.922483.06810393.492482.30710425.822497.896
10447.632498.73510514.742522.84910584.262555.11710620.592554.19310650.832545.042
#Mann= 3 , 0 , 0
9349.111  0.1131       09349.111  0.1131       010650.83  0.1131       0
#XS Ineff= 2 , 0
       0                               0
Bank Sta=9349.111,10650.83
Exp/Cntr=0.3,0.1

Type RM Length L Ch R = 1 ,4682.598,466.474900,466.474900,466.474900
XS GIS Cut Line= 6
548448.809795858 764205.73894095548598.689713087764364.081401962
548727.512763806764538.772542581548846.713235403 764836.26857655
548897.084081335764922.170864576 549188.18806412765258.620728388
#Sta/Elev= 30
9349.1012626.0249428.4542578.6059442.7852565.1799500.858 2537.449527.8882539.621
9567.1922551.1139577.2722550.3149594.0192539.4629619.6672543.496 9625.19 2541.14
9632.4922537.122 9666.892500.4579707.6582452.5339732.1272433.694 9743.312426.216
9756.0262423.709  9803.12421.25510083.272423.12110221.852497.818 10246.92502.212
10284.632492.01210315.792491.15510362.542522.928 10443.32584.88110483.222603.922
10512.862605.11110557.312582.40310616.572567.09710632.462565.37610650.922568.207
#Mann= 3 , 0 , 0
9349.101  0.0201       09349.101  0.0201       010650.92  0.0201       0
#XS Ineff= 2 , 0
       0                               0
Bank Sta=9349.101,10650.92
Exp/Cntr=0.3,0.1

Type RM Length L Ch R = 1 ,4216.123,780.803600,780.803600,780.803600
XS GIS Cut Line= 6
548428.965482862765097.386809397548575.969339961765130.485375767
548733.644718854765148.999327757548876.599296404765179.491698077
548946.332441503765205.846910708549068.013695561765273.128881074
#Sta/Elev= 30
9770.4182461.9289776.6822462.6189838.7062426.1179848.8952424.1299869.2742422.343
9879.4632421.9439889.6532422.3189899.8422421.25510121.922421.25610132.062426.357
 10142.22432.42710152.342441.22210172.962460.73910193.632476.74810203.962485.902
10208.42 2489.0910256.642522.03810267.332527.54710278.022534.28810288.712542.994
10298.432549.427 10310.52555.45210321.662564.00310332.822569.801 10378.12591.486
10389.772597.76910413.122605.84710424.792609.14410436.462610.68710439.982610.308
#Mann= 3 , 0 , 0
9770.418  0.0189       09770.418  0.0189       010439.98  0.0189       0
#XS Ineff= 2 , 0
       0                               0
Bank Sta=9770.418,10439.98
Exp/Cntr=0.3,0.1

Type RM Length L Ch R = 1 , 3435.32,780.803600,780.803600,780.803600
XS GIS Cut Line= 6
547887.004218735765558.061567454547989.242749517765602.078728121
548088.615652718765652.108209098548300.711624217765771.309755467
548473.614798943765902.939365643548541.090538973765949.571457738
#Sta/Elev= 30
 9565.51 2520.789585.1022515.6639606.8772499.8959633.6322484.7249661.3142477.382
9672.2022471.1719683.3172466.7629705.5552454.3359716.8542449.9669739.2462443.169
9761.6372439.629 9772.272434.9769784.0292425.6679807.0242425.3569830.1532421.255
10085.412421.35110098.022425.58210123.442439.29510148.872448.06110161.582453.803
10174.292456.07110199.722465.43910225.142469.15210237.862474.26810262.652480.822
 10274.82486.86610286.962489.33210311.272499.92310323.432502.37710330.832505.521
#Mann= 3 , 0 , 0
 9565.51   0.013       0 9565.51   0.013       010330.83   0.013       0
#XS Ineff= 2 , 0
       0                               0
Bank Sta=9565.51,10330.83
Exp/Cntr=0.3,0.1

Type RM Length L Ch R = 1 ,2654.516,1093.686100,1093.686100,1093.686100
XS GIS Cut Line= 6
547472.487307445767462.234468498547698.548029367767180.196101122
548084.698981507766611.816084611 548342.22959428766407.970584781
548439.567751591766300.266389478548628.955027619765962.111855461
#Sta/Elev= 30
 8749.122577.9158824.3392548.8198850.6232528.7248863.7662514.7278928.4282473.988
8979.3072510.5539029.4542540.9629088.2342567.4629110.6972572.2639157.1112565.945
  9165.72562.2659177.8692545.4569209.7512541.2249238.7182522.9489275.2282511.189
9351.6912496.6949395.313 2500.69 9490.742463.8639516.7832447.6869550.3812435.405
9621.9512432.6649645.1882422.2079657.7692421.25510337.482421.26410374.662440.244
10387.06 2440.4610433.212453.03410500.012492.58110534.572505.53210661.55 2531.96
#Mann= 3 , 0 , 0
 8749.12   0.018       0 8749.12   0.018       010661.55   0.018       0
#XS Ineff= 2 , 0
       0                               0
Bank Sta=8749.12,10661.55
Exp/Cntr=0.3,0.1

Type RM Length L Ch R = 1 , 1560.83,0.000000,0.000000,0.000000
XS GIS Cut Line= 6
549045.980348885767301.001257241549152.078571528767138.435484082
 549432.63412711 766429.40770629 549420.13412711766356.491039649
549648.606349319766137.046595201549802.078571558765814.129928514
#Sta/Elev= 30
 9413.012554.7029432.1182550.4419479.8832521.2459484.4032514.4989491.8242500.855
  9502.72493.5829515.7072493.4839520.9972490.9829539.5892475.3769563.4722449.878
9575.887 2438.179587.3552429.7219599.2962424.6799620.6772421.732 9711.392422.903
9826.1162421.255 10774.92422.14910808.112426.97210830.262438.02510863.472445.947
10885.622449.27410918.832458.97510940.982463.67410974.19 2464.2211007.412484.808
11040.632487.309 11051.72491.62611073.84 2494.2911095.992500.41611130.162501.453
#Mann= 3 , 0 , 0
 9413.01  0.0492       0 9413.01  0.0492       011130.16  0.0492       0
#XS Ineff= 2 , 0
       0                               0
Bank Sta=9413.01,11130.16
Exp/Cntr=0.3,0.1